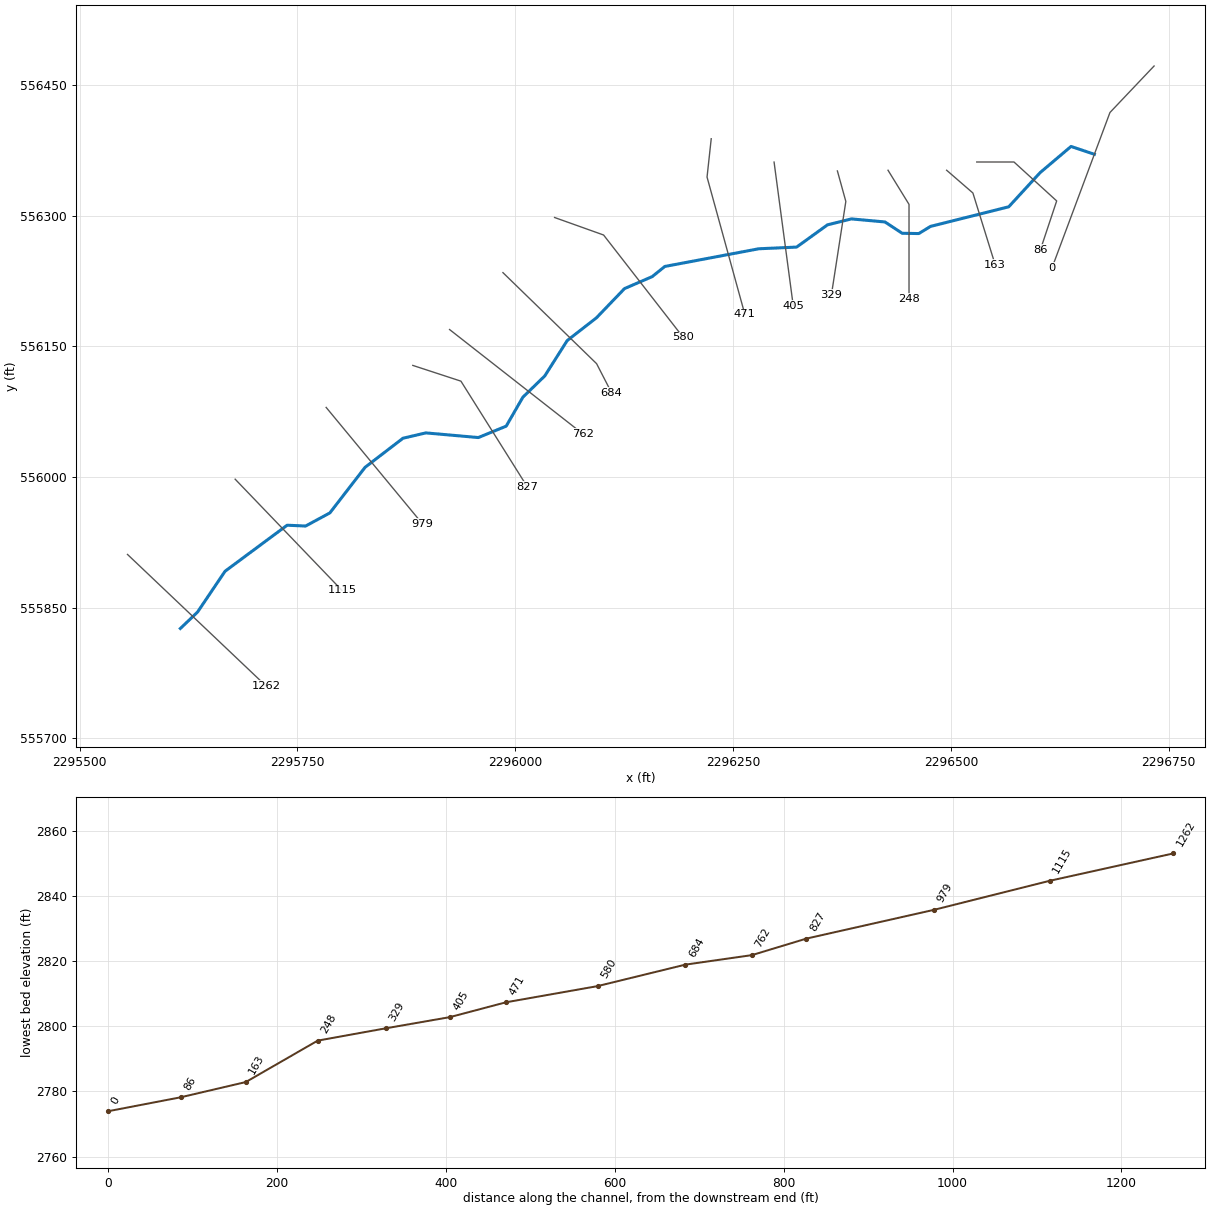
--- ELKCKT1.prj (project) ---

Proj Title=ELKCKT1
Current Plan=p01
Default Exp/Contr=0,0
English Units
Geom File=g01
Flow File=f01
Plan File=p01
Background Map Layer=Inundation Boundary (01pct Value_0)
Background Map Layer=Inundation Boundary (01pct Value_0)
BEGIN DESCRIPTION:
 ----------MODEL BY WOOD PLC 2021----------
Stream Name: Elk Creek Tributary 1
Flood Zone: Enhanced Approximate
Pocahontas County, WV
HEC-RAS Version: RAS 6.1
Vertical Datum: NAVD88
Projection: NAD 1983 StatePlane West Virginia S FIPS 4702 (US Feet)
Terrain: 1-meter LIDAR (FEMA Region III 3DEP collected 2016-2018)
Land Use: 2019 NLCD
Hydrologic Method:
WV SIR2010-5033 regression equations
Model Notes:
KWSELs with Elk Creek
END DESCRIPTION:
DSS Export Rating Curves= 0
DSS Export Rating Curve Sorted= 0
DSS Export Volume Flow Curves= 0
DXF OffsetX= 0
DXF OffsetY= 0
DXF ScaleX= 0
DXF ScaleY= 0

--- ELKCKT1.p01 (plan) ---

Plan Title=Floodplain
Program Version=6.10
Short Identifier=Floodplain
Geom File=g01
Flow File=f01
Subcritical Flow
K Sum by GR= 0
Std Step Tol= 0.01
Critical Tol= 0.01
Num of Std Step Trials= 20
Max Error Tol= 0.3
Flow Tol Ratio= 0.001
Split Flow NTrial= 30
Split Flow Tol= 0.02
Split Flow Ratio= 0.02
Log Output Level= 0
Friction Slope Method= 1
Unsteady Friction Slope Method= 2
Unsteady Bridges Friction Slope Method= 1
Parabolic Critical Depth
Global Vel Dist= 0 , 0 , 0
Global Log Level= 0
CheckData=False
Encroach Param=-1 ,0,0, 0
Mapping Interval=1HOUR
Computation Time Step Use Courant=        0
Computation Time Step Use Time Series=    0
Computation Time Step Count To Double=0
Computation Time Step Max Doubling=0
Computation Time Step Max Halving=0
Computation Time Step Residence Courant=0
Run HTab= 0
Run UNet= 0
Run Sediment= 0
Run PostProcess= 0
Run WQNet= 0
Run RASMapper=-1
UNET Theta= 0
UNET Theta Warmup= 0
UNET ZTol= 0
UNET ZSATol= 0
UNET MxIter= 0
UNET Max Iter WO Improvement= 0
UNET MaxInSteps= 0
UNET DtIC= 0
UNET DtMin= 0
UNET MaxCRTS= 0
UNET WFStab= 0
UNET SFStab= 0
UNET WFX= 1
UNET SFX= 1
UNET Gravity=32.174
UNET 1D Methodology=Finite Difference
UNET DSS MLevel= 1
UNET Pardiso=0
UNET DZMax Abort= 0
UNET Use Existing IB Tables= 0
UNET Froude Reduction=False
UNET Froude Limit= 0
UNET Froude Power= 0
UNET D1 Cores= 0
UNET WindReference=Eulerian
UNET WindDragFormulation=Hsu (1988)
UNET D2 Coriolis=0
UNET D2 Cores= 0
UNET D2 Theta= 1
UNET D2 Theta Warmup= 1
UNET D2 Z Tol= 0.01
UNET D2 Volume Tol= 0.01
UNET D2 Max Iterations= 20
UNET D2 Equation= 0
UNET D2 RampUpFraction=0.1
UNET D2 TimeSlices= 1
UNET D2 Turbulence Formulation=Non-Conservative (original)
UNET D2 Eddy Viscosity=0.3
UNET D2 Transverse Eddy Viscosity=0.1
UNET D2 Smagorinsky Mixing=0
UNET D2 BCVolumeCheck=0
UNET D2 Cores=0
UNET D2 SolverType=PARDISO (Direct)
UNET D2 Minimum Iterations= 2147483647
UNET D2 Maximum Iterations= 2147483647
UNET D2 Restart Number= 10
UNET D2 Relaxation Coeff=1.3
UNET D2 SOR Precondition Iterations= 10
UNET D2 ILUT Maximum Fill= 8
UNET D2 ILUT Tolerance=1E-08
UNET D1D2 MaxIter= 0
UNET D1D2 ZTol=0.01
UNET D1D2 QTol=0.1
UNET D1D2 MinQTol=1
Write IC File= 0
Write IC File at Fixed DateTime=0
Write IC File at Sim End=0
Echo Input=False
Echo Parameters=False
Echo Output=False
Write Detailed= 0
HDF Write Warmup=0
HDF Write Time Slices=0
HDF Flush=0
HDF Compression= 1
HDF Chunk Size= 1
HDF Spatial Parts= 1
HDF Use Max Rows=0
HDF Fixed Rows= 1
Calibration Method= 0
Calibration Iterations= 20
Calibration Max Change=0.05
Calibration Tolerance=0.2
Calibration Maximum=1.5
Calibration Minimum=0.5
Calibration Optimization Method= 1
WQ AD Non Conservative
WQ ULTIMATE=-1
WQ Max Comp Step=1HOUR
WQ Output Interval=15MIN
WQ Output Selected Increments= 0
WQ Output face flow=0
WQ Output face velocity=0
WQ Output face area=0
WQ Output face dispersion=0
WQ Output cell volume=0
WQ Output cell surface area=0
WQ Output cell continuity=0
WQ Output cumulative cell continuity=0
WQ Output face conc=0
WQ Output face dconc_dx=0
WQ Output face courant=0
WQ Output face peclet=0
WQ Output face adv mass=0
WQ Output face disp mass=0
WQ Output cell mass=0
WQ Output cell source sink temp=0
WQ Output nsm pathways=0
WQ Output nsm derived pathways=0
WQ Create Restart=0
WQ Fixed Restart=0
WQ System Summary=0
WQ Write To DSS=0
Sorting and Armoring Iterations= 10
XS Update Threshold= 0.02
Bed Roughness Predictor= 0
Hydraulics Update Threshold= 0.02
Energy Slope Method= 1
Volume Change Method= 1
Sediment Retention Method= 0
Sediment TS Multiplier= 1
Warm Up Method= 0
XS Weighting Method= 0
Number of US Weighted Cross Sections= 1
Number of DS Weighted Cross Sections= 1
Upstream XS Weight=0
Main XS Weight=1
Downstream XS Weight=0
Number of DS XS's Weighted with US Boundary= 1
Upstream Boundary Weight= 1
Weight of XSs Associated with US Boundary= 0
Number of US XS's Weighted with DS Boundary= 1
Downstream Boundary Weight= 0.5
Weight of XSs Associated with DS Boundary= 0.5
Percentile Method= 0
Sediment Output Level= 3
Mass or Volume Output= 0
Output Increment Type= 1
Profile and TS Output Increment= 1
Transport Output Increment 1
XS Output Flag= 0
XS Output Increment= 10
Read HDF5 Sediment Hotstart= 0
Sediment Hotstart Type= 0
Write Gradation File= 0
Read Gradation Hotstart= 0
Write HDF5 File= 1
Write Binary Output= 1
Write DSS Sediment File= 0
DSS Sediment Output Type= 1
SV Curve= 0
Specific Gage Flag= 0
Subcell Erosion Methods= 0
Subcell Deposition Methods= 0
Advection Scheme= 1
Matrix Solver= 0
Implicit Weighting Factor= 1
Maximum Outer Loop Convergence Iterations= 5
Convergence Maximum Absolute= 0.001
Convergence RMSE= 0.0001
Grain Fractions Max Abs Error= 0.001
Max Subgrid Regions= 1
Max Subgrid Length Scale= 3.402823E+38
Initial Layer Thickness= 3.402823E+38
Min Layer Thickness= 3.402823E+38
Max Layer Thickness= 3.402823E+38
Number of Layers= 5

--- ELKCKT1.f01 (steady flow) ---

Flow Title=Flow
Program Version=6.10
Number of Profiles= 6
Profile Names=01pct,10pct,04pct,02pct,0_2pct,01plus
River Rch & RM=ELKCKT1,Main            ,1262
     523     275     367     442     732     774
River Rch & RM=ELKCKT1,Main            ,0
     973     525     691     827    1350    1440
Boundary for River Rch & Prof#=ELKCKT1,Main            , 1
Up Type= 0
Dn Type= 1
Dn Known WS=2778.27
Boundary for River Rch & Prof#=ELKCKT1,Main            , 2
Up Type= 0
Dn Type= 1
Dn Known WS=2777.14
Boundary for River Rch & Prof#=ELKCKT1,Main            , 3
Up Type= 0
Dn Type= 1
Dn Known WS=2777.63
Boundary for River Rch & Prof#=ELKCKT1,Main            , 4
Up Type= 0
Dn Type= 1
Dn Known WS=2777.97
Boundary for River Rch & Prof#=ELKCKT1,Main            , 5
Up Type= 0
Dn Type= 1
Dn Known WS=2779.08
Boundary for River Rch & Prof#=ELKCKT1,Main            , 6
Up Type= 0
Dn Type= 1
Dn Known WS=2779.27
DSS Import GetInterval= 0
DSS Import GetPeak= 0
DSS Import FillOption= 0

--- ELKCKT1.g01 (geometry) ---

Geom Title=Geometry
Program Version=6.10

River Reach=ELKCKT1         ,Main
Reach XY= 30
2295615.55303623 555826.081979232295635.25115955555844.882138476
2295666.87609631 555891.814131232295738.14990389555944.641125306
2295759.31193505555943.6850904822295787.14783739555958.718853056
2295827.57590614556011.0740633162295871.11289255556044.470978141
2295897.33003172556050.6028556382295957.59008181556045.254113063
2295989.59493905 556058.35284014 2296008.7199008 556091.56504406
 2296033.8340238556115.9511501492296059.62891972 556156.61215806
2296093.19184472556182.6970796442296125.38206905 556216.22194697
 2296157.1959818556229.999150395 2296171.6841418556241.655951232
2296279.54372561 556261.95023335 2296322.9822897556263.888107495
2296358.37642672556289.4178019032296385.85438312556296.232284736
2296424.38901697556292.7299960552296444.12815072556279.745113894
2296463.20685272556279.4101408122296476.65695706556287.629940644
2296566.46287981556310.1528614762296602.42901522 556349.32699573
2296637.96109639  556379.41814292296664.73564914556370.406021804

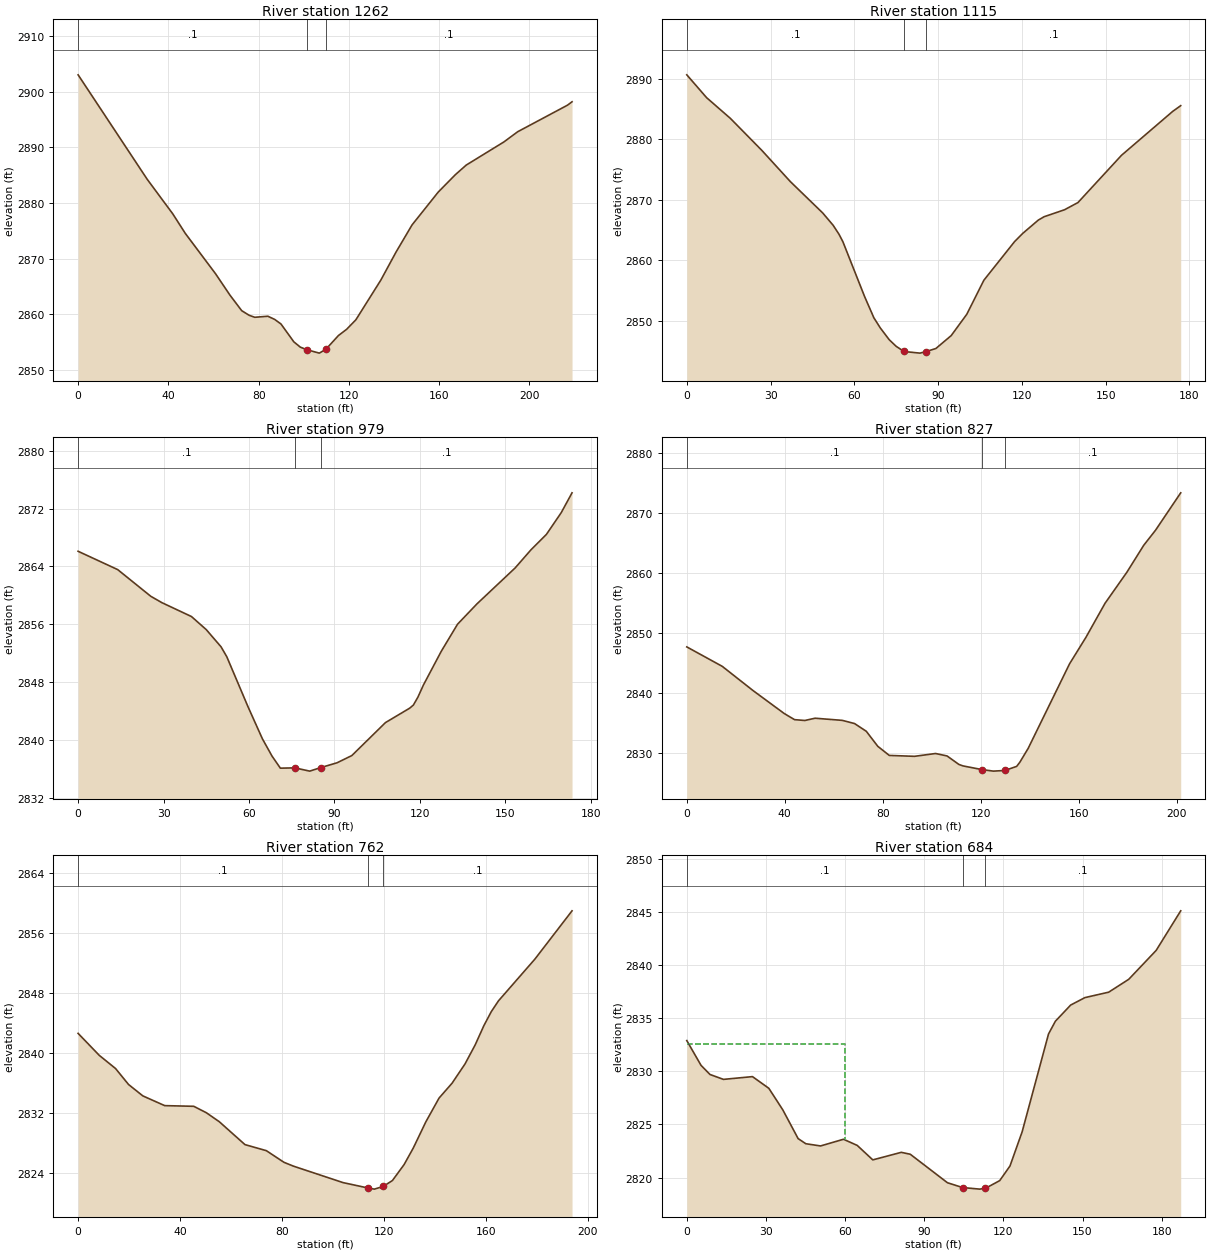
Type RM Length L Ch R = 1 ,1262    ,147,146.7,146.1
XS GIS Cut Line= 2
2295554.88383403555911.0840686652295713.60858707555760.396011984
#Sta/Elev= 30
       0 2903.04    30.6 2884.28    41.9 2878.09    47.5 2874.55    60.9  2867.3
    67.3 2863.45    72.5 2860.66    75.8 2859.83    78.3 2859.47    84.1 2859.66
    87.1 2859.09    89.9 2858.27    95.6 2855.06    98.5  2854.1   101.5 2853.63
   106.9 2853.03   109.8 2853.72   115.4  2856.2     119 2857.31   123.1 2859.02
   134.2 2866.18   140.9 2871.19     148 2876.07   159.6 2881.97   167.2  2885.1
     172 2886.82   188.7 2890.98   194.8 2892.81   216.9 2897.59   218.9  2898.2
#Mann= 3 ,-1,0
       0      .1       0   101.5    .045       0   109.8      .1       0
Bank Sta=101.5,109.8
XS Rating Curve= 0 ,0
Exp/Cntr(USF)=0,0
Exp/Cntr=0.3,0.1

Type RM Length L Ch R = 1 ,1115    ,136.5,136.4,134.7
XS GIS Cut Line= 2
2295678.44804051555997.4785544952295801.00765994555869.895999839
#Sta/Elev= 30
       0 2890.66     7.1 2886.88    15.6 2883.46    26.9 2878.15    37.1 2872.99
    48.7  2867.8    52.4 2865.78    54.5  2864.3    55.9 2863.06    63.7 2853.96
      67 2850.47    69.3 2848.79    72.5 2846.84      75 2845.74    77.8 2844.89
    83.5 2844.62    85.72844.879    89.2 2845.38    94.7 2847.52   100.3 2851.06
   106.4 2856.68   117.4 2863.07   120.3 2864.42   125.9 2866.63     128 2867.19
   135.3 2868.34   140.1 2869.53   155.7 2877.35     174  2884.6   176.9 2885.56
#Mann= 3 ,-1,0
       0      .1       0    77.8    .045       0    85.7      .1       0
Bank Sta=77.8,85.7
XS Rating Curve= 0 ,0
Exp/Cntr(USF)=0,0
Exp/Cntr=0.3,0.1

Type RM Length L Ch R = 1 ,979     ,152,151.5,149.7
XS GIS Cut Line= 2
2295782.92509314556079.8546921462295893.42966804555946.244615223
#Sta/Elev= 30
       0  2866.1    13.9 2863.57    25.5 2859.89    29.4 2859.01    39.8 2857.09
      45 2855.28    50.2  2852.9    52.2 2851.54    59.6 2844.68    64.7 2840.21
    68.1 2837.81      71 2836.16    76.1  2836.2    81.3 2835.75    85.2 2836.24
    90.9  2836.9    96.1  2837.9   107.9 2842.45   116.4 2844.44   117.7 2844.87
   119.3 2845.97   121.2 2847.62   127.5  2852.3   133.2 2856.03     140 2858.83
   153.4 2863.79     159 2866.31   164.4 2868.43   169.6 2871.43   173.4 2874.17
#Mann= 3 ,-1,0
       0      .1       0    76.1    .045       0    85.2      .1       0
Bank Sta=76.1,85.2
XS Rating Curve= 0 ,0
Exp/Cntr(USF)=0,0
Exp/Cntr=0.3,0.1

Type RM Length L Ch R = 1 ,827     ,60.5,64.6,67
XS GIS Cut Line= 3
2295882.37921055556128.074870284  2295937.631498556109.992303482
2296013.98011338555988.437271094
#Sta/Elev= 30
       0 2847.63    14.5 2844.38    27.1 2840.33    39.8 2836.51      44 2835.49
    48.2 2835.35    52.4 2835.73    63.5 2835.37    68.5 2834.84    73.3 2833.55
      78 2831.04    82.7 2829.52      93 2829.37   101.6 2829.84   106.3 2829.43
   111.1 2828.02   112.8 2827.77   120.5 2827.16   125.2  2826.9   129.9 2827.01
   134.7 2827.69     136 2828.38   139.4 2830.69   156.3  2844.8     163 2849.23
   170.8 2854.91   179.7 2860.08   186.6 2864.59   191.4 2867.09   201.7 2873.34
#Mann= 3 ,-1,0
       0      .1       0   120.5    .045       0   129.9      .1       0
Bank Sta=120.5,129.9
XS Rating Curve= 0 ,0
Exp/Cntr(USF)=0,0
Exp/Cntr=0.3,0.1

Type RM Length L Ch R = 1 ,762     ,79.8,78.8,77.6
XS GIS Cut Line= 2
2295924.57186642 556169.262939112296077.26909719 556049.71708081
#Sta/Elev= 30
       0 2842.61     8.3 2839.68    14.7 2837.92    19.8 2835.79    25.4 2834.27
      34 2832.97    45.4 2832.88    50.3 2832.03    55.4 2830.83    65.5 2827.77
    73.9 2826.96    80.8 2825.41    84.5  2824.9     104  2822.7   113.7 2821.99
   116.3 2821.83   119.82822.192   123.4 2822.98     128 2825.12   131.6 2827.33
   136.5  2830.8   141.7 2833.98   146.8 2835.96   151.9 2838.54   155.9 2841.09
   159.3 2843.65   162.2 2845.51     165 2846.94   179.3 2852.51   193.9 2858.96
#Mann= 3 ,-1,0
       0      .1       0   113.7    .045       0   119.8      .1       0
Bank Sta=113.7,119.8
XS Rating Curve= 0 ,0
Exp/Cntr(USF)=0,0
Exp/Cntr=0.3,0.1

Type RM Length L Ch R = 1 ,684     ,105,104,102.5
XS GIS Cut Line= 3
2295985.85167614556234.561097005 2296093.3424899556130.084044373
2296110.42046966556096.932671904
#Sta/Elev= 30
       0 2832.88     5.4 2830.55     8.8 2829.69    13.9 2829.23    24.9 2829.49
    31.1 2828.39    36.4 2826.36    42.2 2823.66    45.1 2823.18    50.7 2822.97
    59.4  2823.6    64.6 2823.02    70.5 2821.66    81.3 2822.37    84.7 2822.19
    98.8 2819.51   104.5 2819.06     111 2818.91   113.22818.986   118.6 2819.71
   122.5 2821.09   127.1  2824.3   137.1  2833.5   139.7  2834.7   145.5 2836.22
   150.9 2836.92   159.9 2837.43   167.5 2838.64   177.9 2841.36   187.2 2845.08
#Mann= 3 ,-1,0
       0      .1       0   104.5    .045       0   113.2      .1       0
#XS Ineff= 2 , 0
           60.04 2832.59
Permanent Ineff=
       F       F
Bank Sta=104.5,113.2
XS Rating Curve= 0 ,0
Exp/Cntr(USF)=0,0
Exp/Cntr=0.3,0.1

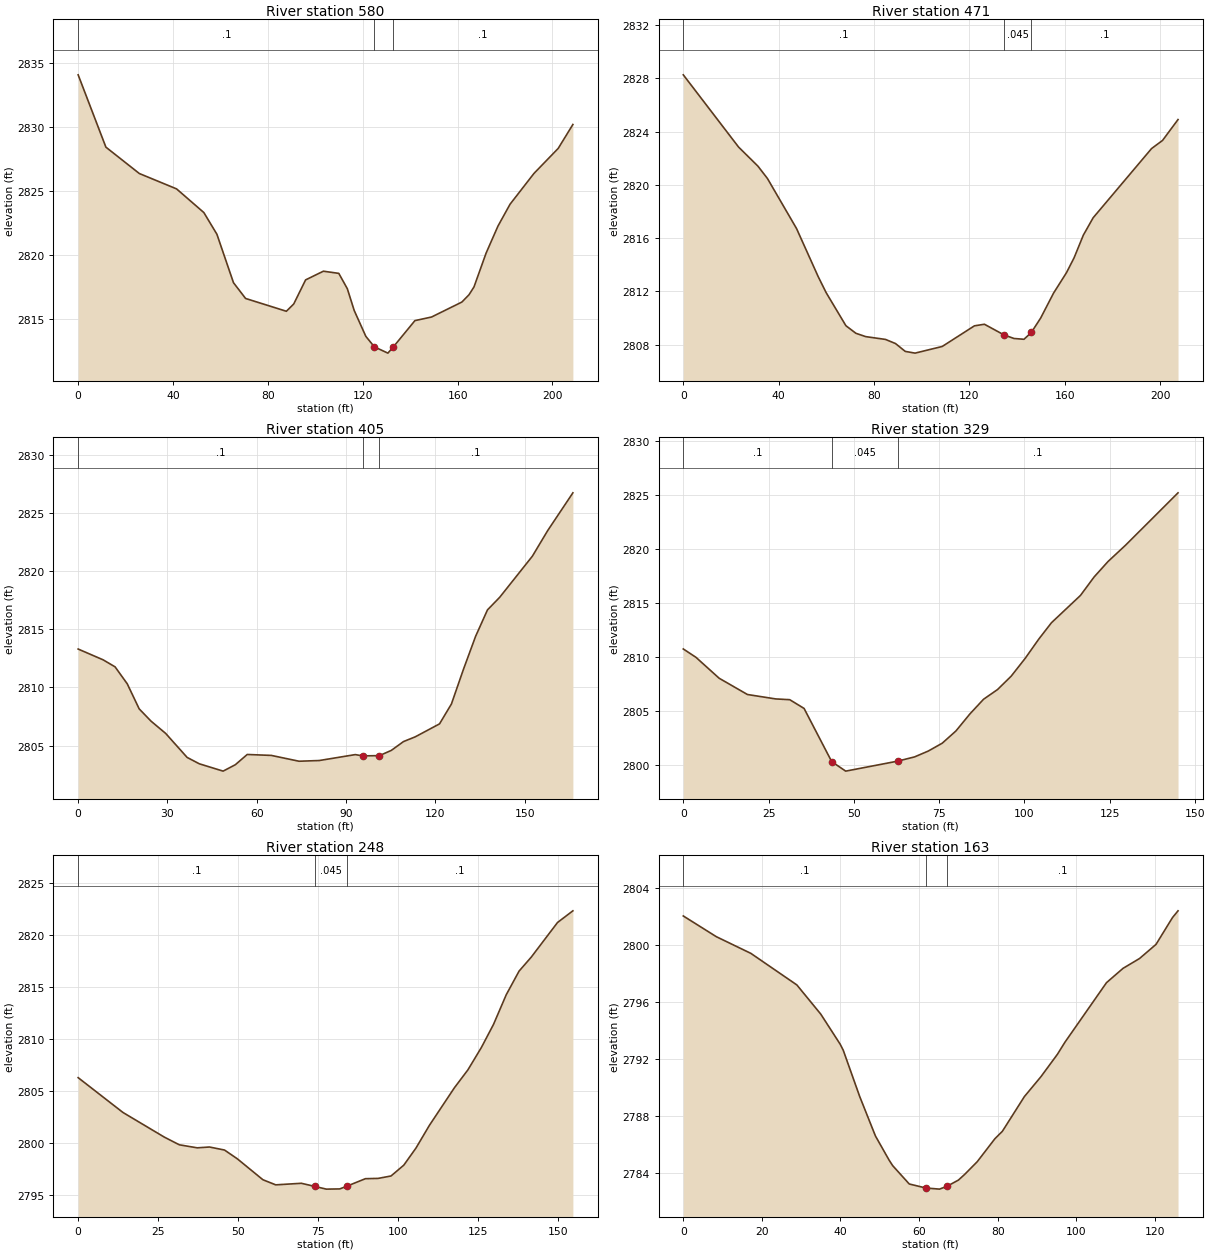
Type RM Length L Ch R = 1 ,580     ,111.3,108.4,103.9
XS GIS Cut Line= 3
2296045.12231176 556297.850080812296101.37918626 556277.75833992
2296192.79660731556160.221655709
#Sta/Elev= 30
       0 2834.06    11.7 2828.41    25.8 2826.35    41.5 2825.15      53  2823.3
    58.5 2821.61    65.5 2817.82    70.6 2816.59    87.8 2815.59    90.9 2816.16
    95.9 2818.04   103.4 2818.72   109.9 2818.55   113.5 2817.35   116.4 2815.65
   121.3 2813.63   124.9 2812.81   130.6 2812.32  132.882812.804     142 2814.86
     149 2815.14   161.8 2816.31   164.8 2816.88   166.9 2817.49     172 2820.13
     177 2822.24   182.1 2823.95   192.2 2826.36   202.4 2828.31   208.6 2830.18
#Mann= 3 ,-1,0
       0      .1       0   124.9    .045       0  132.88      .1       0
Bank Sta=124.9,132.88
XS Rating Curve= 0 ,0
Exp/Cntr(USF)=0,0
Exp/Cntr=0.3,0.1

Type RM Length L Ch R = 1 ,471     ,69.4,66.6,64.6
XS GIS Cut Line= 3
2296224.94339274556388.2629148192296220.13312246556344.265358708
2296263.47590153556186.920176017
#Sta/Elev= 30
       0 2828.27    23.2 2822.84    31.3 2821.41    35.3 2820.48    47.5 2816.72
    56.6  2813.1    59.9 2811.91    68.2 2809.42    72.4 2808.85    76.5  2808.6
    84.8 2808.39      89 2808.08    93.1 2807.49    97.2 2807.36   108.6 2807.86
   122.1 2809.41   126.3 2809.53   134.5 2808.73   138.7 2808.46   142.9  2808.4
     146 2808.92   149.9    2810   155.3 2811.87   160.7  2813.4   163.9 2814.52
   167.8 2816.23   171.9 2817.53   196.4 2822.73     201 2823.34   207.5 2824.91
#Mann= 3 ,-1,0
       0      .1       0   134.5    .045       0     146      .1       0
Bank Sta=134.5,146
XS Rating Curve= 0 ,0
Exp/Cntr(USF)=0,0
Exp/Cntr=0.3,0.1

Type RM Length L Ch R = 1 ,405     ,76.1,75.5,71
XS GIS Cut Line= 2
2296297.08373205556361.4931252522296319.05405072556196.715735272
#Sta/Elev= 30
       0 2813.29     8.4 2812.36    12.4 2811.76    16.5  2810.3    20.5 2808.15
    24.5 2807.09    29.4 2806.04    36.6 2803.98    40.7 2803.43    48.7  2802.8
    52.8 2803.35    56.8 2804.23    64.9 2804.15    74.2 2803.65      81 2803.71
    93.1 2804.22    95.6 2804.11   101.2 2804.13   105.2 2804.58   109.3 2805.34
   113.2 2805.74   121.4 2806.86   125.4 2808.57   129.4 2811.52   133.5 2814.37
   137.5 2816.65   141.6 2817.73   152.6 2821.27   157.7 2823.45   166.2 2826.71
#Mann= 3 ,0,0
       0      .1       0    95.6    .045       0   101.2      .1       0
Bank Sta=95.6,101.2
XS Rating Curve= 0 ,0
Exp/Cntr(USF)=0,0
Exp/Cntr=0.3,0.1

Type RM Length L Ch R = 1 ,329     ,78.1,80.9,81.4
XS GIS Cut Line= 3
 2296369.7746366 556351.289076922296379.45128394556316.279018306
2296362.86839377556208.841990445
#Sta/Elev= 26
       0 2810.71     3.7 2809.94    10.5    2808    18.8 2806.49    27.1 2806.08
    31.2 2806.01    35.4  2805.2    43.5 2800.27    47.6 2799.39    62.9 2800.32
    67.8 2800.71    71.8 2801.25    75.9 2801.98    79.9 2803.11      84 2804.69
      88 2806.05    92.1 2806.95    96.1 2808.19   100.2 2809.84   104.2 2811.63
   107.9 2813.14   116.4 2815.67   120.4 2817.38   124.5 2818.82   129.6 2820.32
     145 2825.18
#Mann= 3 ,0,0
       0      .1       0    43.5    .045       0    62.9      .1       0
Bank Sta=43.5,62.9
XS Rating Curve= 0 ,0
Exp/Cntr(USF)=0,0
Exp/Cntr=0.3,0.1

Type RM Length L Ch R = 1 ,248     ,81.6,85.2,87.7
XS GIS Cut Line= 3
2296427.86997573556352.097781215 2296451.9800648556312.918886478
 2296451.9800648556204.423485669
#Sta/Elev= 30
       0 2806.29      14 2802.95    26.9 2800.59    31.6 2799.85    37.2 2799.56
      41 2799.64    45.7 2799.35    49.7 2798.51    57.7  2796.5    61.7 2796.01
    69.7 2796.16    73.9 2795.86    77.5  2795.6    81.7 2795.62   83.82 2795.87
    89.7  2796.6    93.7 2796.63    97.7 2796.86   101.7  2797.9   105.5 2799.54
   109.7 2801.72   117.5 2805.32   121.7 2807.03   125.9 2809.17   129.7 2811.39
   133.7 2814.25   137.7 2816.51   141.5 2817.85   149.7 2821.17   154.5 2822.29
#Mann= 3 ,-1,0
       0      .1       0    73.9    .045       0   83.82      .1       0
Bank Sta=73.9,83.82
XS Rating Curve= 0 ,0
Exp/Cntr(USF)=0,0
Exp/Cntr=0.3,0.1

Type RM Length L Ch R = 1 ,163     ,72.8,77,81.5
XS GIS Cut Line= 3
2296495.17730772556352.0977812152296525.31491905556325.978518057
2296550.82287542556243.864012243
#Sta/Elev= 30
       0 2802.02     8.4 2800.57    17.2  2799.4    28.9 2797.19      35 2795.14
    39.9 2793.05    40.7 2792.62    44.9 2789.37    48.9 2786.61    52.4 2784.91
    53.3 2784.53    57.5 2783.25    61.7 2782.97    65.2 2782.89    67.1 2783.09
      70 2783.52    71.6 2783.92    74.8 2784.81    79.3 2786.42    81.2 2786.94
    86.8 2789.37      91 2790.76    95.2 2792.33    97.1 2793.17   107.7 2797.35
   111.9 2798.35   116.1 2799.04   120.3 2800.03   124.5 2801.91   125.9 2802.38
#Mann= 3 ,-1,0
       0      .1       0    61.7    .045       0    67.1      .1       0
Bank Sta=61.7,67.1
XS Rating Curve= 0 ,0
Exp/Cntr(USF)=0,0
Exp/Cntr=0.3,0.1

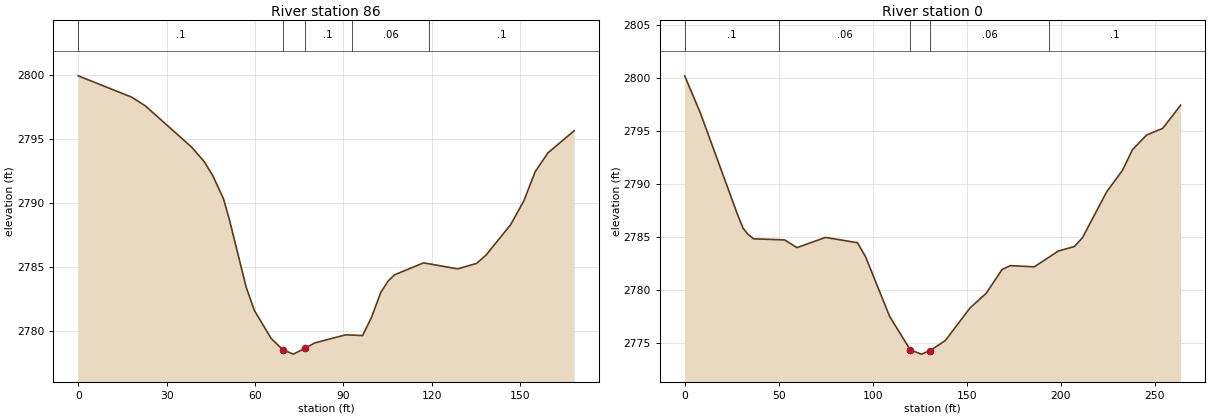
Type RM Length L Ch R = 1 ,86      ,96.4,86,72.9
XS GIS Cut Line= 4
2296529.70417624556361.557946272 2296572.4678636556361.557946272
2296621.47793225556316.8722954382296602.73878835556260.654863743
#Sta/Elev= 30
       0 2799.96    18.1  2798.3    22.8 2797.61    38.5 2794.39    42.8 2793.25
    45.7 2792.15    49.3 2790.35    51.3 2788.73      57 2783.45    59.8 2781.62
    65.5 2779.44    69.4 2778.57      73 2778.22    76.8 2778.66    80.3  2779.1
    90.8 2779.73    96.5 2779.67    99.5 2781.07   102.7 2783.05   105.1 2783.91
   107.3 2784.41   117.2 2785.35   128.8 2784.88   135.2 2785.31   138.3 2785.93
   146.7 2788.32   151.2 2790.18   155.1 2792.48   159.4 2793.94   168.3 2795.67
#Mann= 5 ,-1,0
       0      .1       0    69.4    .045       0    76.8      .1       0
   92.76     .06       0  119.09      .1       0
Bank Sta=69.4,76.8
XS Rating Curve= 0 ,0
Exp/Cntr(USF)=0,0
Exp/Cntr=0.3,0.1

Type RM Length L Ch R = 1 ,0       ,131.8,,131.8
XS GIS Cut Line= 3
2296733.28918436556471.7608263642296682.63550526556418.383831183
2296616.18659289556240.278959509
#Sta/Elev= 30
       0 2800.17     8.3 2796.69    28.1  2787.1    31.1 2785.79    33.7 2785.23
    36.6 2784.81    53.2  2784.7    59.7 2783.98    74.9 2784.94    91.9 2784.44
    96.2 2783.11     109 2777.49     120 2774.33   125.9 2773.94   130.4 2774.26
   138.6 2775.22   151.7 2778.29   160.3 2779.67   168.8 2781.92   173.1 2782.28
   185.9 2782.17   198.7 2783.66   207.2 2784.08   211.5 2784.91   224.3 2789.21
   232.8 2791.27   238.1 2793.21   245.6 2794.59   254.2 2795.22   263.7  2797.4
#Mann= 5 ,-1,0
       0      .1       0      50     .06       0     120    .045       0
   130.4     .06       0  193.59      .1       0
Bank Sta=120,130.4
XS Rating Curve= 0 ,0
Exp/Cntr(USF)=0,0
Exp/Cntr=0.3,0.1
LCMann Table=0

Chan Stop Cuts=-1
Use User Specified Reach Order=0
Composite Channel Slope=5